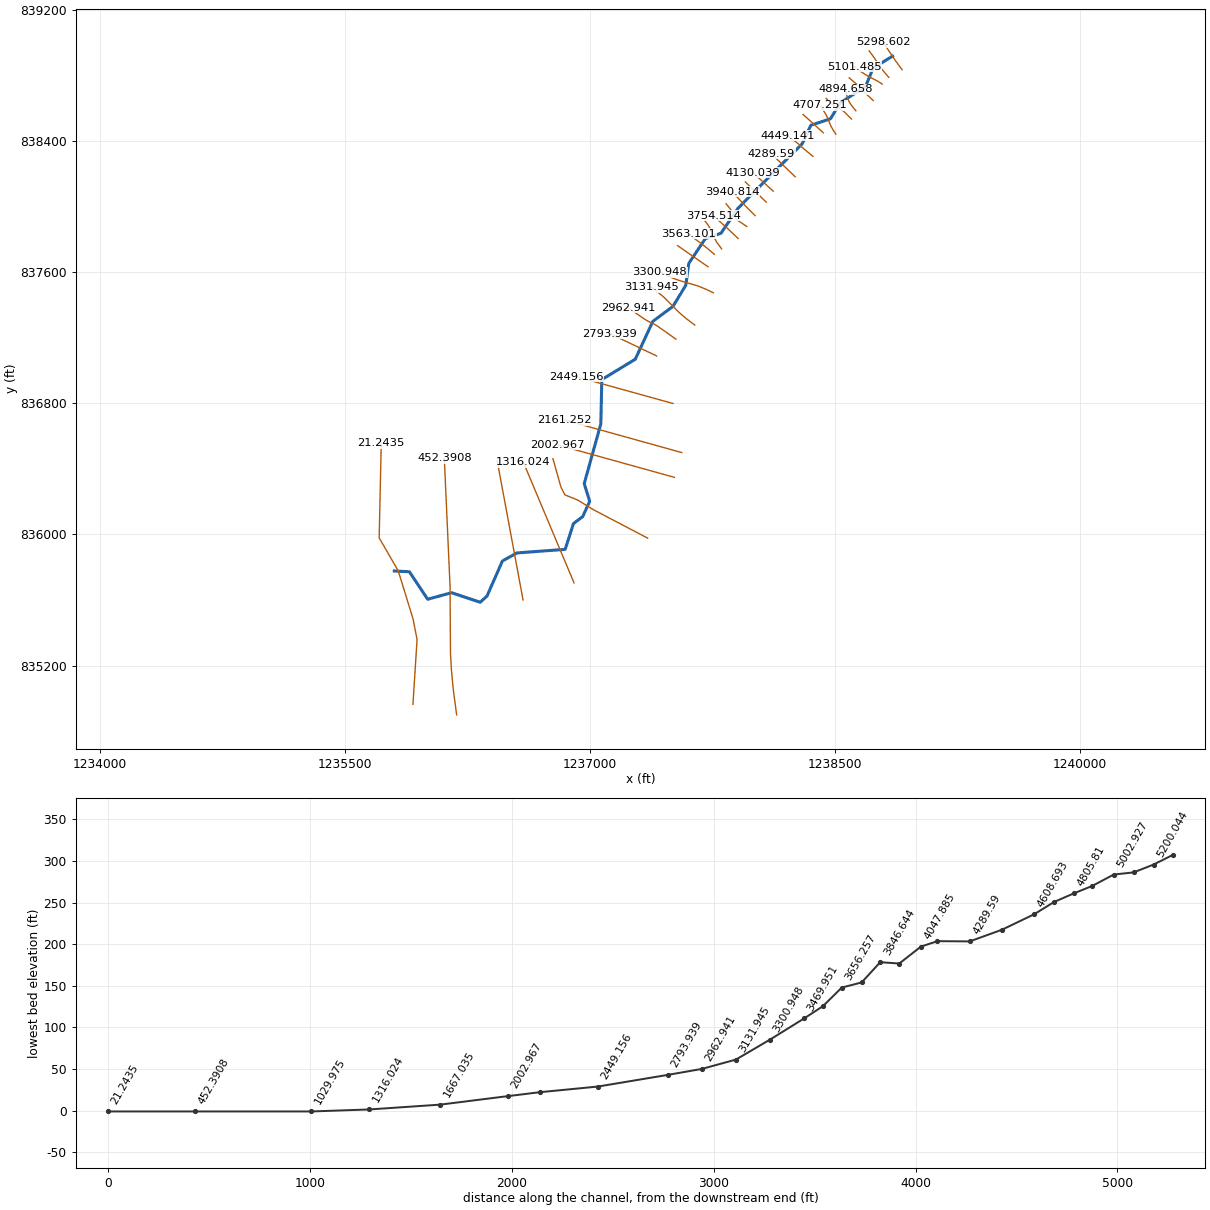
--- 29_ras.prj (project) ---

Proj Title=29
Current Plan=p01
Default Exp/Contr=0.3,0.1
English Units
Geom File=g01
Flow File=f01
Plan File=p01
Y Axis Title=Elevation
X Axis Title(PF)=Main Channel Distance
X Axis Title(XS)=Station
BEGIN DESCRIPTION:
RFD model 29 exported to HEC-RAS
END DESCRIPTION:

--- 29_ras.p01 (plan) ---

Plan Title=Plan 01
Program Version=4.10
Short Identifier=Plan 01
Geom File=g01
Flow File=f01
Subcritical Flow
Calc Critical at every XS
Secant Critical Depth

--- 29_ras.f01 (steady flow) ---

Flow Title=Flow 01
Program Version=5.01
Number of Profiles= 5
Profile Names=10yr,25yr,50yr,100yr,500yr
River Rch & RM=29,30,5298.602
  232.03  418.42  603.13  829.34 1527.94
River Rch & RM=29,30,5101.485
  250.94  453.31  654.48  901.56 1668.91
River Rch & RM=29,30,4894.658
  259.47  469.05  677.69  934.24 1732.92
River Rch & RM=29,30, 4805.81
  269.81  488.17  705.89  973.97 1810.91
River Rch & RM=29,30,4707.251
  385.31  702.59 1023.58 1423.75 2705.12
River Rch & RM=29,30,4449.141
  409.35  747.43 1090.29 1518.62    2896
River Rch & RM=29,30, 4289.59
  421.96  770.96 1125.33 1568.51 2996.65
River Rch & RM=29,30,4130.039
  427.36  781.04 1140.35  1589.9 3039.88
River Rch & RM=29,30,4047.885
  433.95  793.37 1158.72 1616.07 3092.78
River Rch & RM=29,30,3940.814
  444.14  812.41 1187.11 1656.53 3174.69
River Rch & RM=29,30,3846.644
  454.33  831.45 1215.51 1697.03 3256.79
River Rch & RM=29,30,3754.514
   466.9  854.96  1250.6  1747.1 3358.44
River Rch & RM=29,30,3563.101
  478.86  877.35 1284.03 1794.84  3455.5
River Rch & RM=29,30,3469.951
  488.42  895.26 1310.78 1833.05 3533.32
River Rch & RM=29,30,3300.948
  506.33  928.83 1360.96 1904.78 3679.63
River Rch & RM=29,30,3131.945
  515.88  946.73 1387.74 1943.08 3757.87
River Rch & RM=29,30,2962.941
  538.53  989.23 1451.35 2034.13 3944.23
River Rch & RM=29,30,2793.939
  550.45  1011.6 1484.85  2082.1 4042.63
River Rch & RM=29,30,2449.156
  586.13 1078.67 1585.39 2226.25 4339.04
River Rch & RM=29,30,2161.252
  611.08  1125.6 1655.82 2327.35 4547.57
River Rch & RM=29,30,2002.967
  702.29 1297.57 1914.37 2699.25 5319.04
River Rch & RM=29,30,1667.035
  734.19 1357.83 2005.15 2830.09 5591.92
River Rch & RM=29,30,1316.024
  742.45 1373.45 2028.69 2864.04 5662.86
River Rch & RM=29,30,1029.975
  825.53 1530.69 2265.98 3206.74 6381.43
River Rch & RM=29,30,452.3908
  871.38 1617.62 2397.39 3396.86 6782.01
River Rch & RM=29,30, 21.2435
  883.12  1639.9  2431.1 3445.67 6885.05
Boundary for River Rch & Prof#=29,30,1
Up Type= 0
Dn Type= 2
Boundary for River Rch & Prof#=29,30,2
Up Type= 0
Dn Type= 2
Boundary for River Rch & Prof#=29,30,2
Up Type= 0
Dn Type= 2
Boundary for River Rch & Prof#=29,30,2
Up Type= 0
Dn Type= 2
Boundary for River Rch & Prof#=29,30,2
Up Type= 0
Dn Type= 2

--- 29_ras.g01 (geometry) ---

Geom Title=29
Program Version=4.10

River Reach=29,30
Reach XY= 30
1238852.78695849 838916.429436961238733.65792697  838842.5455837
1238686.99127072838730.0456183191238532.82464645838631.712318578
1238472.82466122838534.2123491191238352.82469531838495.045697513
1238299.49137433838381.712399249 1237906.9914781837989.212526691
1237802.71833565837836.8167951411237706.15819832837803.379254152
1237605.32489019837652.5459683011237586.99155833 837519.21267493
1237508.65824425837390.8793817951237385.32494445837299.212745817
1237277.82496927837068.3794838411237072.82502585836944.212859861
1237066.99168633836674.2129398021236965.32503886836310.046383731
1236998.65835927836202.5464145061236956.15836901836109.213109983
1236899.49171774836066.7131241861236848.65839473 835909.21317224
1236553.65848075835887.5465205851236464.49183883835838.379871063
1236370.32519357 835625.046603511236328.65853802835586.713282724
1236152.82525804 835645.046603961236006.99196636835605.046620038
 1235895.3253374835772.5465738211235802.72844667835777.577536687

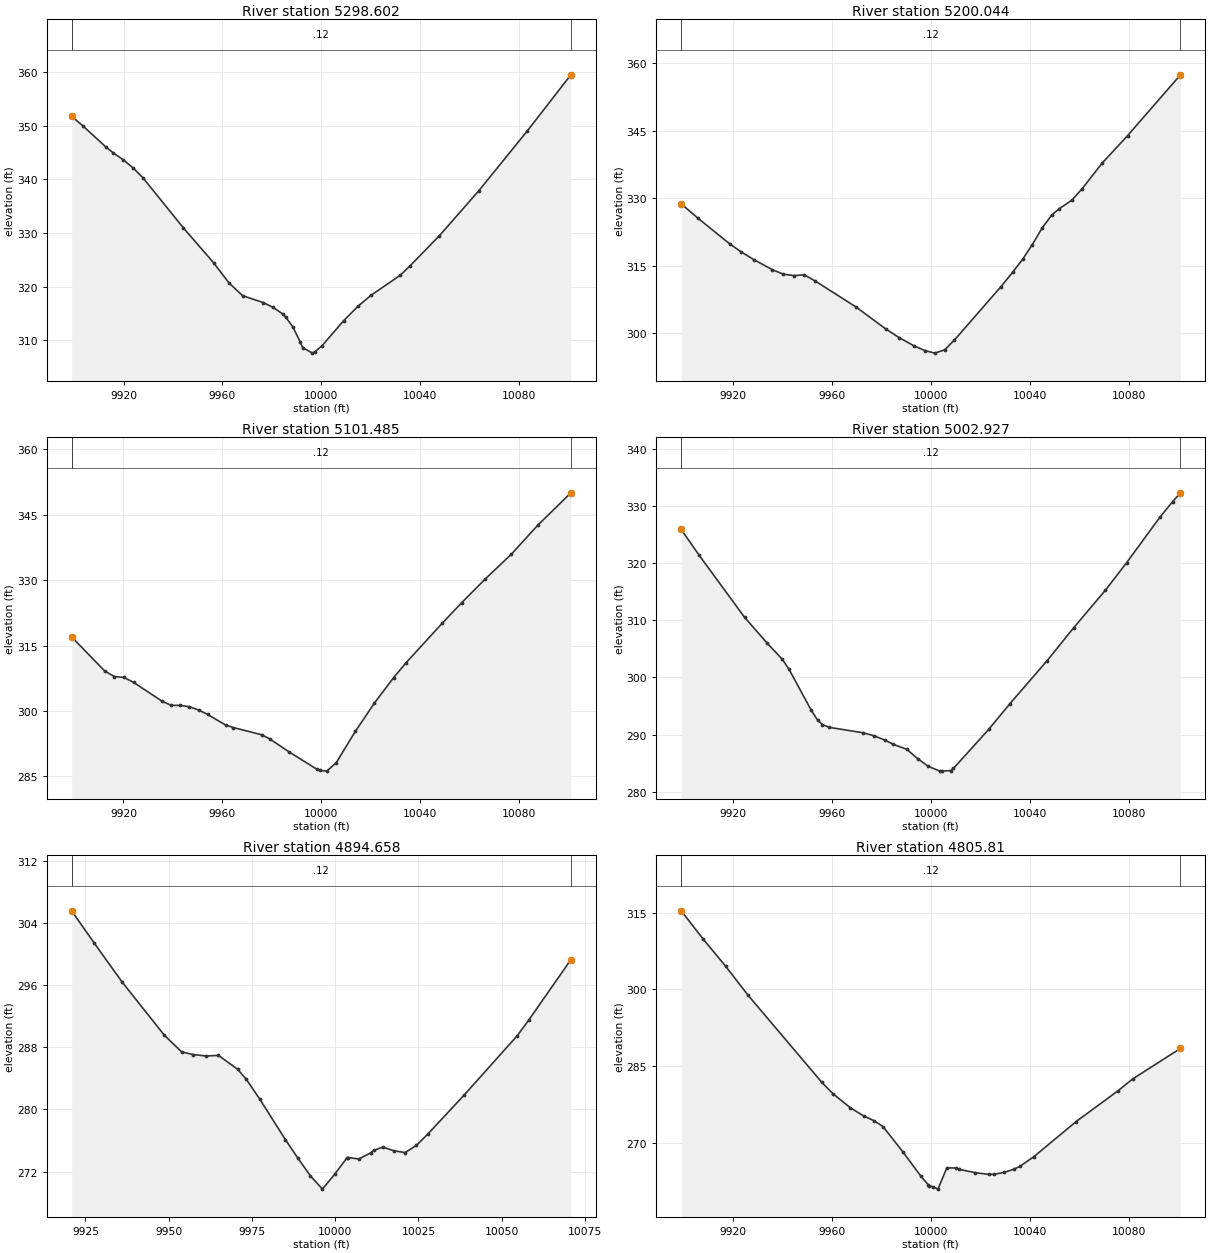
Type RM Length L Ch R = 1 ,5298.602,98.558500,98.558500,98.558500
XS GIS Cut Line= 5
1238910.89832159838833.8897907551238869.65707897838889.881928237
1238852.51035463 838915.042537431238851.40005896838916.706040819
1238795.66834284838999.733989303
#Sta/Elev= 30
9899.011351.74039903.465349.99869912.895  346.019915.689344.98169919.764343.6587
9923.839  342.159927.913340.25039944.212  330.949956.436324.44049962.684320.6675
9968.216318.28469976.598316.99789980.569 316.0969984.539314.84089985.676314.2537
9988.509312.47529991.502 309.6669992.479308.6122 9996.45307.57869997.328307.7828
10000.41309.000310009.09313.635810014.98316.361810020.17 318.37310032.02322.1189
10035.97323.881110047.83 329.48710063.63337.795810083.39349.0266   10101359.4767
#Mann= 3 , 0 , 0
9899.011    0.12       09899.011    0.12       0   10101    0.12       0
#XS Ineff= 2 , 0
       0                               0
Bank Sta=9899.011,10101
Exp/Cntr=0.3,0.1

Type RM Length L Ch R = 1 ,5200.044,98.558500,98.558500,98.558500
XS GIS Cut Line= 6
1238829.94915215838786.5139910791238788.87034704838834.432320417
1238768.04509155838864.8181126221238766.91572377838866.468727179
1238739.85279303838907.1049936931238709.53512452838948.326584709
#Sta/Elev= 30
9899.047328.77679905.672325.66129918.636319.89559923.426318.05559928.467316.3729
9935.922314.14839940.243 313.1659944.565312.83789948.886312.99929953.207311.6516
 9969.83305.82769981.762300.98499987.207299.0521 9993.01297.28339997.672296.1672
10001.64295.603110005.58296.330310009.53298.489510028.37310.377810033.18 313.617
10037.12 316.43610041.06319.7151   10045323.377310048.94326.3087 10051.9327.6652
10057.06329.607310061.13332.079810069.28337.805610079.59343.932710100.99 357.455
#Mann= 3 , 0 , 0
9899.047    0.12       09899.047    0.12       010100.99    0.12       0
#XS Ineff= 2 , 0
       0                               0
Bank Sta=9899.047,10100.99
Exp/Cntr=0.3,0.1

Type RM Length L Ch R = 1 ,5101.485,98.558500,98.558500,98.558500
XS GIS Cut Line= 6
1238789.20746002838745.9380773891238759.75660292838764.957368193
1238710.31004723838789.5074623791238671.94707735838813.092364776
1238645.72638494838830.668551974 1238618.1314863838852.329899229
#Sta/Elev= 30
9899.037316.97759912.387309.18629916.292307.90359920.198307.69369924.103306.5639
9935.713302.20619939.376301.29069943.039301.28579946.701300.97839950.364300.2292
9954.027299.21789961.353296.77639964.371296.21369976.005294.53279979.126293.6136
9986.994290.62499998.358286.60249999.623286.375110002.25286.212510006.11 288.172
10013.82295.344510021.53301.821810029.24307.621410034.34 311.07610048.86320.0647
10056.76324.7886 10066.3330.233810076.93335.949110087.55342.558610100.98350.0101
#Mann= 3 , 0 , 0
9899.037    0.12       09899.037    0.12       010100.98    0.12       0
#XS Ineff= 2 , 0
       0                               0
Bank Sta=9899.037,10100.98
Exp/Cntr=0.3,0.1

Type RM Length L Ch R = 1 ,5002.927,108.268300,108.268300,108.268300
XS GIS Cut Line= 6
1238734.33873338838645.5186434981238687.42005676 838689.58714529
1238663.55148739838716.0195384681238662.23447822838717.524691897
  1238646.455303838734.0736721491238587.46159345838783.732531772
#Sta/Elev= 30
9899.016325.87699906.246321.38129924.646310.51289933.648306.05899939.792303.2268
9942.651301.40099951.653294.22249954.168292.53729956.154291.7467 9958.96291.2566
9972.565290.30979976.986289.78819981.406289.04069984.892288.27249990.247287.4271
9994.668285.7833    9999284.436810003.54283.618410004.41283.600910008.08283.7021
10009.16284.074310023.42290.907310032.04295.429610046.88302.835110057.78308.6842
10070.64315.257910079.22320.077510092.73328.059310097.82330.755910100.98332.2866
#Mann= 3 , 0 , 0
9899.016    0.12       09899.016    0.12       010100.98    0.12       0
#XS Ineff= 2 , 0
       0    9984                       0
Bank Sta=9899.016,10100.98
Exp/Cntr=0.3,0.1

Type RM Length L Ch R = 1 ,4894.658,88.848700,88.848700,88.848700
XS GIS Cut Line= 5
1238628.27664855838582.8955899161238605.12717812838611.247092998
1238589.31763602838633.8701983661238577.00942361838659.606146995
1238563.98859028838715.335313661
#Sta/Elev= 30
9920.843 305.5819927.604301.44169936.075296.3722 9948.68289.56539953.868287.4165
9957.253287.06959961.266286.8819 9964.95286.95559970.678285.18559973.274283.9014
9977.276281.38059985.045276.11059988.783273.73729992.533271.4618 9996.17269.7325
9999.807271.624210003.44273.702410003.99273.805610007.08273.612610010.72274.4124
 10011.6274.7183 10014.3275.148210017.67274.667210021.03274.4447 10024.4275.3647
10027.77276.797310038.66281.809610054.73289.5148 10058.1291.4752 10070.8299.2887
#Mann= 3 , 0 , 0
9920.843    0.12       09920.843    0.12       0 10070.8    0.12       0
#XS Ineff= 2 , 0
       0                               0
Bank Sta=9920.843,10070.8
Exp/Cntr=0.3,0.1

Type RM Length L Ch R = 1 , 4805.81,98.558500,98.558500,98.558500
XS GIS Cut Line= 6
1238601.38689911838532.4608824211238552.95543457838580.633871168
1238537.96758134838590.9540602591238493.65985829838614.513780485
1238471.93188416838632.5240054511238446.20418192838658.672316233
#Sta/Elev= 30
9899.071315.32789907.988309.79959917.047304.51249926.106298.86939955.981281.8578
9960.398279.68639967.427276.93969973.037275.2806 9977.02274.41119980.649273.2756
9988.643268.37229995.831263.6827    9999261.90279999.394261.6944   10001261.5115
10002.87261.064410006.47265.2134 10010.1265.185810011.37264.929310017.88264.2835
10023.57263.926210025.66263.959910029.55264.319210033.44264.914910036.03265.5063
10041.72267.411210058.77274.242210075.62 280.21510081.62282.546610100.94288.4958
#Mann= 3 , 0 , 0
9899.071    0.12       09899.071    0.12       010100.94    0.12       0
#XS Ineff= 2 , 0
       0                               0
Bank Sta=9899.071,10100.94
Exp/Cntr=0.3,0.1

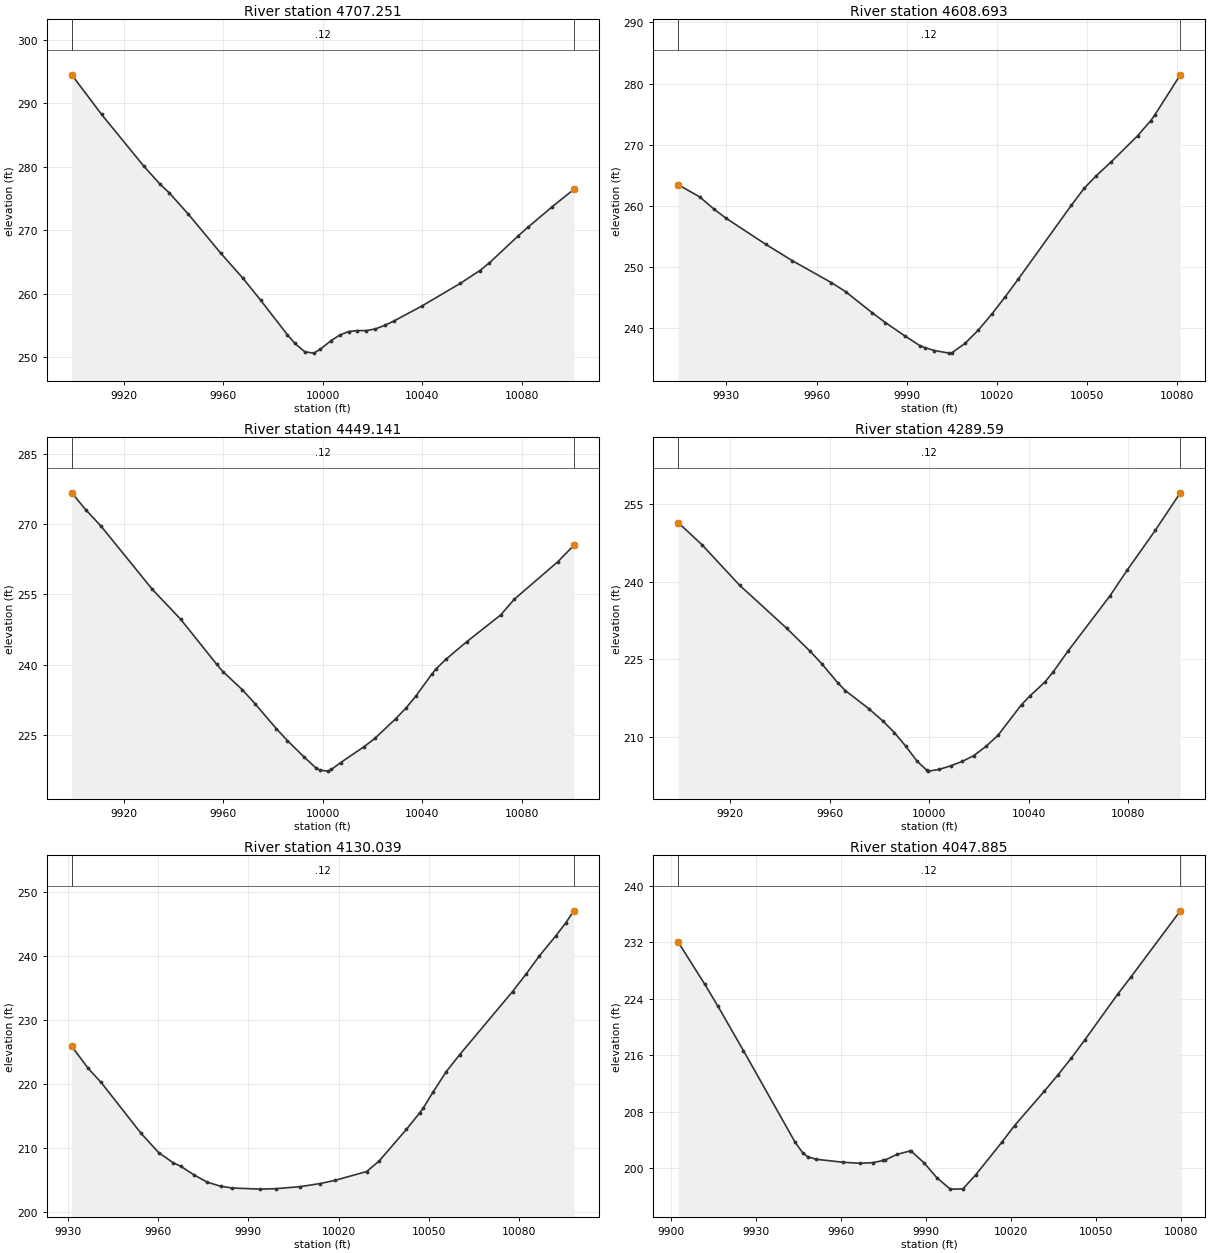
Type RM Length L Ch R = 1 ,4707.251,98.558500,98.558500,98.558500
XS GIS Cut Line= 6
1238506.07016569838440.4289130611238489.74656221  838464.4656748
1238474.47126139838491.3084613081238453.40412679838543.415892927
1238444.84114874838560.6906250351238409.17321015838616.784016534
#Sta/Elev= 30
 9899.05294.45989911.027288.23059928.105280.04119934.499277.26299938.274275.8672
9945.824272.5716 9958.99 266.3649967.915262.41419975.021258.96419985.679253.5741
9988.797252.15959992.785250.85219996.338250.6414    9999251.261610003.37252.6275
10006.88253.500510010.39254.0367 10013.9254.189810017.51 254.18910021.17254.4588
10024.83255.006410028.49255.681310039.79258.047610055.34261.640710063.11263.6326
   10067264.860310078.67269.142810082.55270.486210092.29273.711310100.96 276.425
#Mann= 3 , 0 , 0
 9899.05    0.12       0 9899.05    0.12       010100.96    0.12       0
#XS Ineff= 2 , 0
       0                               0
Bank Sta=9899.05,10100.96
Exp/Cntr=0.3,0.1

Type RM Length L Ch R = 1 ,4608.693,159.551300,159.551300,159.551300
XS GIS Cut Line= 2
1238428.95820833838448.9623391241238304.82626389838560.941505791
#Sta/Elev= 29
9913.921263.44039921.052261.4553 9925.77259.47229929.889257.94349943.145 253.665
9951.982250.98539964.954247.41179969.656245.94079978.493242.49129982.911240.8758
9989.444238.67449994.342237.12019996.167236.7624 9999.24236.298210004.14235.8742
   10005 235.91910009.42237.461910013.84239.641710018.26242.219210022.68245.0125
 10027.1 247.95310044.77260.045510049.19262.909710053.12264.908710058.03267.1488
10066.86271.435710071.28273.942410072.71274.9264 10081.1281.4234
#Mann= 3 , 0 , 0
9913.921    0.12       09913.921    0.12       0 10081.1    0.12       0
#XS Ineff= 2 , 0
       0                               0
Bank Sta=9913.921,10081.1
Exp/Cntr=0.3,0.1

Type RM Length L Ch R = 1 ,4449.141,159.551300,159.551300,159.551300
XS GIS Cut Line= 6
1238365.61661783838305.050909334   1238307.83174838352.603019708
1238289.14521131 838369.449244941238287.69992764838370.831690277
1238270.53702511838385.9437853231238208.50185304838431.756805859
#Sta/Elev= 30
9899.006276.69999904.561273.13159910.796269.57589931.448256.07079942.801 249.719
9957.265240.11769959.796 238.5449967.591234.68749972.754231.66469981.326226.3384
9985.743223.81619992.409220.33269997.309217.93399998.995 217.48210002.16217.2919
10003.44 217.64810007.12219.100610016.56222.501710020.93224.283610029.28228.4657
10033.36230.707610037.44 233.328 10043.9238.060310045.59239.140710049.42 241.133
10057.83244.893210071.51 250.61510077.04253.995210094.54261.997910100.99265.5056
#Mann= 3 , 0 , 0
9899.006    0.12       09899.006    0.12       010100.99    0.12       0
#XS Ineff= 2 , 0
       0                               0
Bank Sta=9899.006,10100.99
Exp/Cntr=0.3,0.1

Type RM Length L Ch R = 1 , 4289.59,159.551300,159.551300,159.551300
XS GIS Cut Line= 4
1238256.61814167838180.5809153691238184.63031922838249.987903385
1238183.15845723 838251.342016491238111.28485658838320.866323251
#Sta/Elev= 30
9899.002251.46159908.503247.20719923.686239.33949942.593231.00159952.047226.5393
9956.774224.10229963.191220.42069966.227218.91149975.681215.39759981.421212.9757
9985.978210.76259990.536208.14439995.093205.2195    9999203.47189999.636 203.292
10004.09 203.633 10008.8204.3531 10013.3205.184110017.86206.282310022.96208.1378
10027.68210.250610037.12 216.18510040.68217.945910046.56220.570410049.81222.4931
10055.99226.666810072.64 237.22610079.59242.2223 10090.9249.9399   10101257.2303
#Mann= 3 , 0 , 0
9899.002    0.12       09899.002    0.12       0   10101    0.12       0
#XS Ineff= 2 , 0
       0                               0
Bank Sta=9899.002,10101
Exp/Cntr=0.3,0.1

Type RM Length L Ch R = 1 ,4130.039,82.153700,82.153700,82.153700
XS GIS Cut Line= 2
1238122.53459722838093.0595613461237998.40265277838205.038728013
#Sta/Elev= 30
9931.189225.88859936.561222.5058 9940.98220.24649954.235212.3219 9960.08209.3085
9964.978 207.7059967.491207.15429971.909205.80999976.328204.66739980.746204.0422
 9984.57203.76339994.002203.58869999.264203.661810007.26203.975910013.96204.4668
10018.86204.964310029.35 206.33510033.55207.996810042.61212.928110047.02215.5021
10048.24216.273210051.44218.721610055.86221.940410060.28224.559510077.95234.4595
10082.53237.234510086.79239.973810092.33243.148710095.63245.166410098.37247.0627
#Mann= 3 , 0 , 0
9931.189    0.12       09931.189    0.12       010098.37    0.12       0
#XS Ineff= 2 , 0
       0                               0
Bank Sta=9931.189,10098.37
Exp/Cntr=0.3,0.1

Type RM Length L Ch R = 1 ,4047.885,107.070900,107.070900,107.070900
XS GIS Cut Line= 2
1238079.35317361838026.1426053271237951.74900694838148.972466438
#Sta/Elev= 30
9902.595232.0184 9911.95226.07149916.504223.01719925.611216.65189943.826203.6885
9946.568202.1459 9948.38 201.6019951.299201.2604 9960.76200.84119966.596200.6949
9971.149200.77679974.953201.09129975.703201.17139979.684201.94149984.415202.4468
9984.811202.39739989.365200.74639993.876198.62939998.607197.033510003.03197.0647
10007.58199.078710016.69203.643110021.24206.033610031.72210.890410036.45213.1641
10041.18215.543510045.92218.109410057.67224.666510062.23227.049210079.71236.4483
#Mann= 3 , 0 , 0
9902.595    0.12       09902.595    0.12       010079.71    0.12       0
#XS Ineff= 2 , 0
       0                               0
Bank Sta=9902.595,10079.71
Exp/Cntr=0.3,0.1

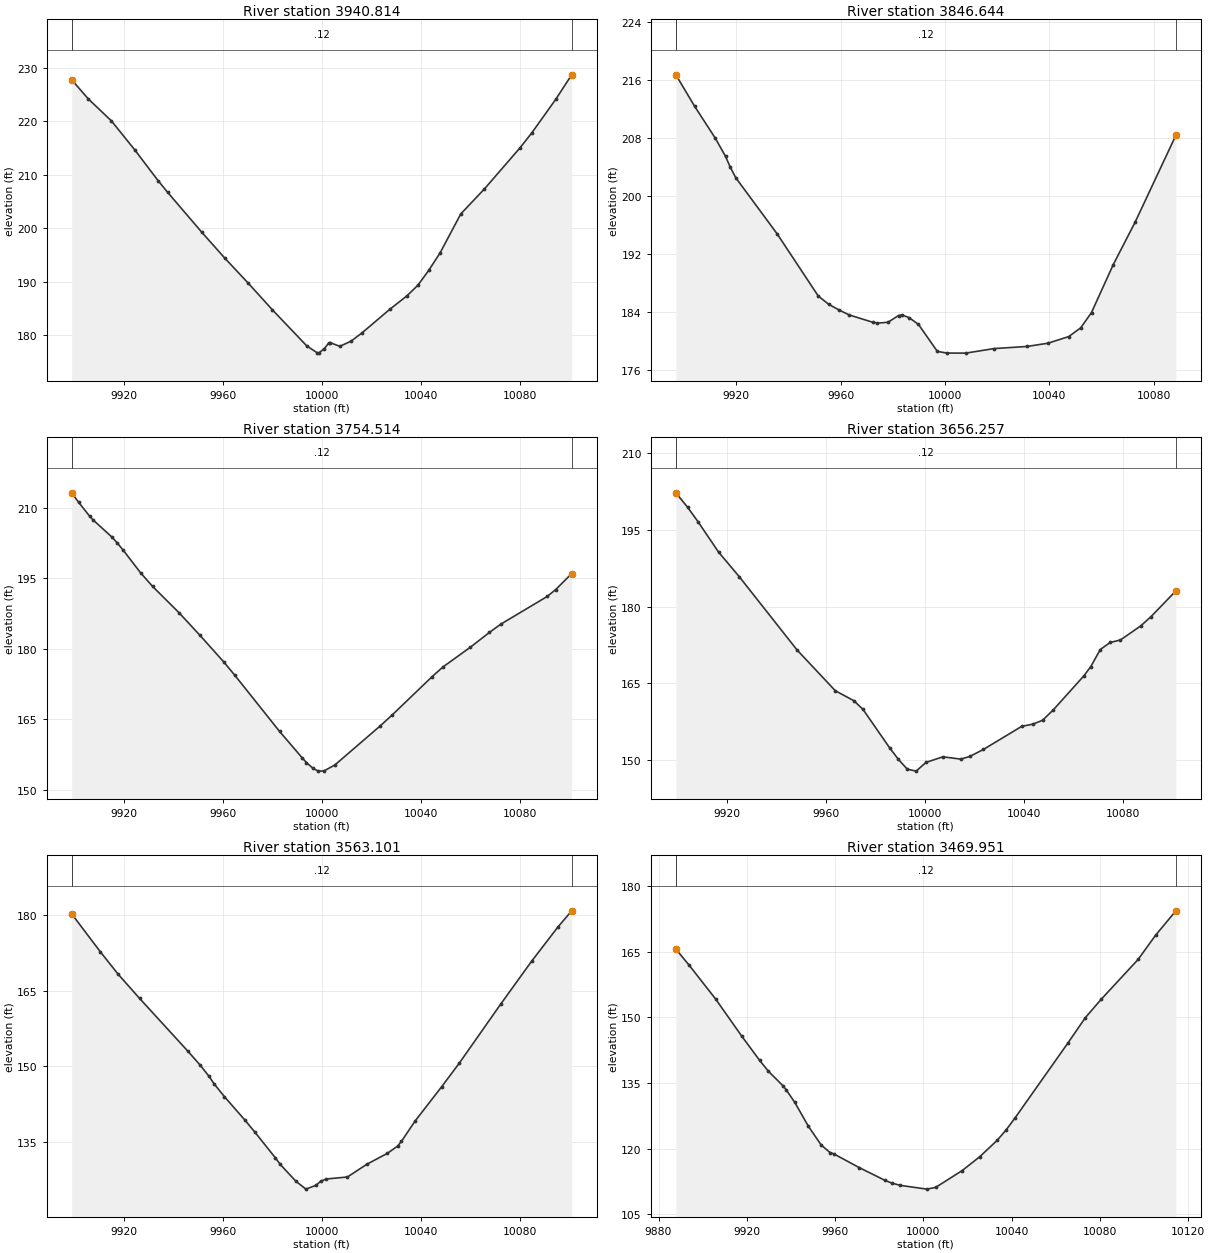
Type RM Length L Ch R = 1 ,3940.814,94.170800,94.170800,94.170800
XS GIS Cut Line= 5
1238011.81871981837943.7371013521237969.19620804837985.208105327
1237941.22038782838014.527223237 1237939.8061743838015.941436842
1237871.31988716838088.787976977
#Sta/Elev= 30
9899.007227.73859905.734224.15679915.059220.05959924.469214.65769933.878208.9212
9937.777206.71199951.509199.29499960.748194.48689970.253189.78829980.114184.7598
9994.016178.01769998.253 176.7299998.768176.6858   10001177.500610002.82178.5603
10003.49178.626710007.32 177.95710011.83178.911210016.33180.481810027.44184.8439
10034.34187.344510038.84189.351510043.35192.216210047.85195.430710056.18202.6801
10065.76207.362210080.13215.036110084.92217.8497 10094.5 224.05310100.98228.6574
#Mann= 3 , 0 , 0
9899.007    0.12       09899.007    0.12       010100.98    0.12       0
#XS Ineff= 2 , 0
       0                               0
Bank Sta=9899.007,10100.98
Exp/Cntr=0.3,0.1

Type RM Length L Ch R = 1 ,3846.644,92.129200,92.129200,92.129200
XS GIS Cut Line= 5
1237960.46253103837877.6852310831237900.75074305837917.780336808
1237890.76810416837931.6692256971237876.22817361837962.702211808
1237833.96833565838016.434850697
#Sta/Elev= 30
9896.827216.76599904.004212.43329911.908208.0407 9915.86205.51269917.689204.0175
9919.812202.54469935.619 194.8319951.426186.22479955.378185.1043 9959.33184.3077
9963.282183.62249972.214182.6197  9974.1182.4941 9978.14182.6099 9982.18183.5433
9983.457183.62489986.183183.25789989.806182.32629997.052178.592610000.68  178.36
10007.92178.350410018.79178.977710031.49179.273910039.46179.719310047.41180.6337
10051.98181.830610056.15183.9552 10064.5190.579810072.85196.411810088.49208.4184
#Mann= 3 , 0 , 0
9896.827    0.12       09896.827    0.12       010088.49    0.12       0
#XS Ineff= 2 , 0
       09982.834                       0
Bank Sta=9896.827,10088.49
Exp/Cntr=0.3,0.1

Type RM Length L Ch R = 1 ,3754.514,98.257100,98.257100,98.257100
XS GIS Cut Line= 6
1237907.33670748837804.5349950261237836.28612422837871.579404321
1237834.57365526837873.1275719731237833.07397959837874.450815292
 1237788.6947198837913.4519157361237759.60529449837942.213338592
#Sta/Elev= 30
9899.002213.11929901.815211.10779906.326208.11129907.803207.29219915.347203.6843
9917.364202.50599919.858200.90879926.925196.07519931.705193.22949942.413187.6225
9950.827182.84639960.388177.22539964.967174.31979983.011162.41179992.032156.8721
9993.851155.80859996.543154.56419998.677153.990610000.95154.040110005.32 155.295
10023.52163.540710028.49165.930110044.63174.078310048.99176.123110060.08180.3201
10067.75183.458310072.41185.230410091.08191.094610094.51192.554610100.99195.9604
#Mann= 3 , 0 , 0
9899.002    0.12       09899.002    0.12       010100.99    0.12       0
#XS Ineff= 2 , 0
       0                               0
Bank Sta=9899.002,10100.99
Exp/Cntr=0.3,0.1

Type RM Length L Ch R = 1 ,3656.257,93.156600,93.156600,93.156600
XS GIS Cut Line= 6
1237806.25673886837741.2490139761237776.22213317837782.355962408
1237764.85939941837803.3409886181237736.77265691837864.891470064
1237720.07701507837891.1931230711237702.87721801837913.666645429
#Sta/Elev= 30
9899.352202.26699904.071199.45259908.245 196.6569916.593190.6836  9924.9185.9026
9948.286171.54159963.738163.56789971.199161.6215  9974.9159.93369985.644152.4248
9989.226150.14099992.807148.23159996.389147.843610000.35 149.54410007.19150.6417
10014.44150.188510018.06150.719510023.58152.089710039.01156.593410043.55157.0357
10047.44157.788410051.84159.853110064.08166.453110066.87168.246710070.76171.6222
10074.75173.003910078.88173.488510087.14176.263610091.27178.069710101.28183.0881
#Mann= 3 , 0 , 0
9899.352    0.12       09899.352    0.12       010101.28    0.12       0
#XS Ineff= 2 , 0
       0                               0
Bank Sta=9899.352,10101.28
Exp/Cntr=0.3,0.1

Type RM Length L Ch R = 1 ,3563.101,93.150000,93.150000,93.150000
XS GIS Cut Line= 6
1237762.11708853837707.9122583821237719.98715764837743.912949764
  1237684.487586837770.8720210381237682.91257603837772.104637609
1237647.65900914837798.6227875291237604.22878725837833.788203944
#Sta/Elev= 30
9899.008180.26689910.581172.73329917.825168.24359926.456163.45829945.933152.9842
9950.983150.16919954.424148.01629956.563146.47649960.683143.95669968.922139.3207
9973.042136.86989981.281131.79219983.276130.4692 9989.52127.1564 9993.64 125.556
9997.759126.3318 9999.54127.0947 10001.9127.570810010.42127.968310018.32130.5213
10026.53132.662910030.64134.095910032.25 135.06610037.71139.068310048.47145.9028
10055.56150.571410072.44162.409610084.96170.945110095.39 177.623   10101180.8681
#Mann= 3 , 0 , 0
9899.008    0.12       09899.008    0.12       0   10101    0.12       0
#XS Ineff= 2 , 0
       0                               0
Bank Sta=9899.008,10101
Exp/Cntr=0.3,0.1

Type RM Length L Ch R = 1 ,3469.951,169.003000,169.003000,169.003000
XS GIS Cut Line= 2
1237723.22904166837632.1220613451237536.88556991837760.948428832
#Sta/Elev= 30
9887.849165.62019893.861 161.9529905.826154.24379917.792145.66969925.769140.2184
9929.758137.72259936.268134.44769937.735133.53929941.723130.60339947.807125.2071
9953.689120.86149957.677119.14139959.345 118.8469970.884115.70059982.422112.8168
9985.597112.16869989.586 111.62910001.55110.771610005.54111.166610017.51114.9881
10025.48118.156410033.46121.938810037.45124.287110041.44126.980310065.37144.0911
10073.34149.9315 10080.5154.126210097.28163.260810105.25168.829210114.39174.3726
#Mann= 3 , 0 , 0
9887.849    0.12       09887.849    0.12       010114.39    0.12       0
#XS Ineff= 2 , 0
       0                               0
Bank Sta=9887.849,10114.39
Exp/Cntr=0.3,0.1

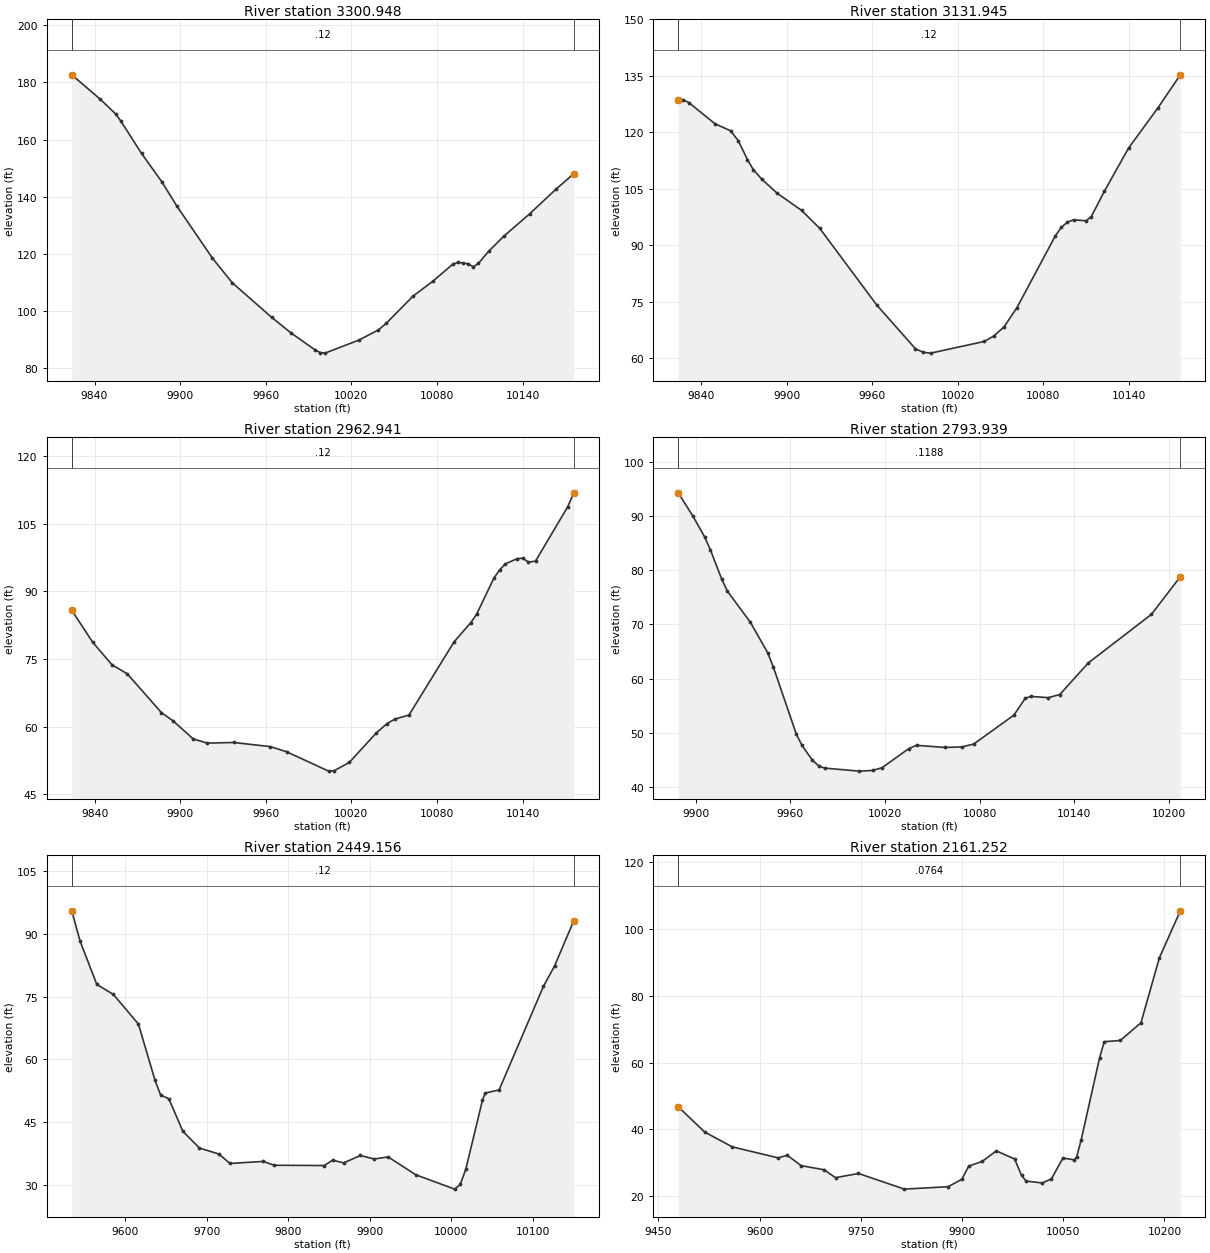
Type RM Length L Ch R = 1 ,3300.948,169.003000,169.003000,169.003000
XS GIS Cut Line= 6
1237755.73263988837473.2603988081237712.33078941837494.369990372
1237661.26534093837515.282289856 1237555.2833295837545.947474367
1237508.83513367837562.1937398831237428.20768746837599.614878976
#Sta/Elev= 30
9824.027 182.6789843.781 174.2349854.726169.03689858.374166.53849872.948155.1838
9887.129145.29169897.765136.71979922.582118.6081 9936.52109.9608 9964.1497.87919
9977.753 92.39829994.73886.428629998.13585.5689710001.5485.3567710025.3289.92425
10038.94 93.455510044.3895.7496210063.27105.303710077.17110.509310091.19116.4826
10094.77117.070610098.34116.845410101.91116.581210105.49115.533810109.06116.7174
10116.21120.946810126.93126.263110145.06134.103410163.42142.669910175.97148.1115
#Mann= 3 , 0 , 0
9824.027    0.12       09824.027    0.12       010175.97    0.12       0
#XS Ineff= 2 , 0
       0                               0
Bank Sta=9824.027,10175.97
Exp/Cntr=0.3,0.1

Type RM Length L Ch R = 1 ,3131.945,169.003100,169.003100,169.003100
XS GIS Cut Line= 6
1237642.17327064837276.6666508731237594.26017866837312.774824863
1237560.71790663837340.6133926031237530.56929368837368.570840015
1237453.80462363 837446.128196561237377.84839363837508.154994404
#Sta/Elev= 30
9824.017128.59269827.309128.67519831.418127.88399849.832122.24019860.734120.3866
9866.186 117.7049872.499112.75729876.607110.08769882.539107.54759893.382103.7809
9910.43699.253979923.22794.45953 9963.28  74.0489990.33262.460049995.943 61.5115
   1000161.3104510038.6664.4251510045.0765.8249910052.41 68.278910061.4973.41186
10088.3692.4719110092.5694.7317810096.8996.1403210101.2296.7435410109.88 96.4777
10113.4997.51856 10122.8104.362910139.67115.7744 10160.3126.487610175.98135.2563
#Mann= 3 , 0 , 0
9824.017    0.12       09824.017    0.12       010175.98    0.12       0
#XS Ineff= 2 , 0
       0                               0
Bank Sta=9824.017,10175.98
Exp/Cntr=0.3,0.1

Type RM Length L Ch R = 1 ,2962.941,169.003000,169.003000,169.003000
XS GIS Cut Line= 6
1237526.91382166837190.6482462371237413.98800692837270.232576731
 1237393.4190454837282.439969304 1237359.1809483837298.389379094
1237332.47361929 837314.164811621237233.09986472 837383.33343386
#Sta/Elev= 30
9824.02185.825249838.75278.695159852.23573.705579862.83471.727969886.91763.07747
9894.94461.277529909.18857.238939919.02756.315429937.66456.452589963.128 55.5382
9974.57354.4015610004.0550.0913510007.6850.1373510018.5852.0235910037.3758.52743
10044.9960.6574910050.4161.6232110060.4262.5548610091.9778.78658 10103.883.09914
10107.7984.92721 10119.992.9417410123.9494.7884810127.9896.1406410136.0697.25784
 10140.197.4089810144.1496.52912 10149.196.7348410171.61108.772210175.98111.9096
#Mann= 3 , 0 , 0
9824.021    0.12       09824.021    0.12       010175.98    0.12       0
#XS Ineff= 2 , 0
       09931.988                       0
Bank Sta=9824.021,10175.98
Exp/Cntr=0.3,0.1

Type RM Length L Ch R = 1 ,2793.939,344.782300,344.782300,344.782300
XS GIS Cut Line= 2
1237408.55890277837088.3575937511237121.01549999837225.076343751
#Sta/Elev= 30
9888.95194.31132 9898.3889.945069905.64686.199199909.27983.831059916.545 78.3489
9920.17776.128459934.709 70.39359945.60764.80631 9949.2462.145579963.77149.78498
9967.40447.651899974.00744.933549978.30243.798419981.935  43.45510003.7342.90146
10012.2143.0300810018.2643.5421210035.1347.0615810040.0647.6748810058.22   47.27
10069.1247.3850110076.3947.9176110101.82 53.246510109.0856.3870510112.7256.70064
10123.6156.4733810130.8857.0491910149.0462.9024910189.0171.8562610207.3478.81548
#Mann= 3 , 0 , 0
9888.951  0.1188       09888.951  0.1188       010207.34  0.1188       0
#XS Ineff= 2 , 0
       0                               0
Bank Sta=9888.951,10207.34
Exp/Cntr=0.3,0.1

Type RM Length L Ch R = 1 ,2449.156,287.904000,287.904000,287.904000
XS GIS Cut Line= 2
1237508.38529166836798.6440520841236914.61720717836962.684850695
#Sta/Elev= 30
 9534.5995.575479544.87988.274049565.30277.948429585.72475.549799616.35868.46565
 9636.7854.968949643.58851.484479653.79950.555779670.817 42.8098 9691.2438.77744
9715.06637.346429728.68135.090249769.52635.570319783.14134.654979844.40834.59039
9854.61935.880119868.23435.220629888.657  36.9959905.67536.152639922.69436.65563
9956.73132.3698910004.3828.9422710011.19 30.0619   1001833.6777410038.4250.18645
10041.8251.9613710058.8452.67277 10113.377.4961210126.9282.37414 10150.693.24212
#Mann= 3 , 0 , 0
 9534.59    0.12       0 9534.59    0.12       0 10150.6    0.12       0
#XS Ineff= 2 , 0
       09930.511                       0
Bank Sta=9534.59,10150.6
Exp/Cntr=0.3,0.1

Type RM Length L Ch R = 1 ,2161.252,158.285000,158.285000,158.285000
XS GIS Cut Line= 2
 1237562.4036655836499.3601979171236845.17276273 836697.92790625
#Sta/Elev= 30
9479.27846.789259518.38539.239429559.23634.79448 9627.3231.493599640.93732.27554
9661.36329.166519695.40527.936699712.42725.567239746.46926.817559814.55422.13539
9879.23522.85586 9899.6625.077149909.87329.036519930.04630.442889950.72433.59199
9977.95831.139799988.17126.223379994.97924.5473710018.8123.9822610032.4325.19834
10049.4531.4296910066.4730.9064910069.8731.8026110076.6836.9868110103.9161.50396
10110.7266.2719710134.55 66.629910165.1971.9389710192.4391.3635710223.49105.4371
#Mann= 3 , 0 , 0
9479.278  0.0764       09479.278  0.0764       010223.49  0.0764       0
#XS Ineff= 2 , 0
       09771.888        10051.57       0
Bank Sta=9479.278,10223.49
Exp/Cntr=0.3,0.1

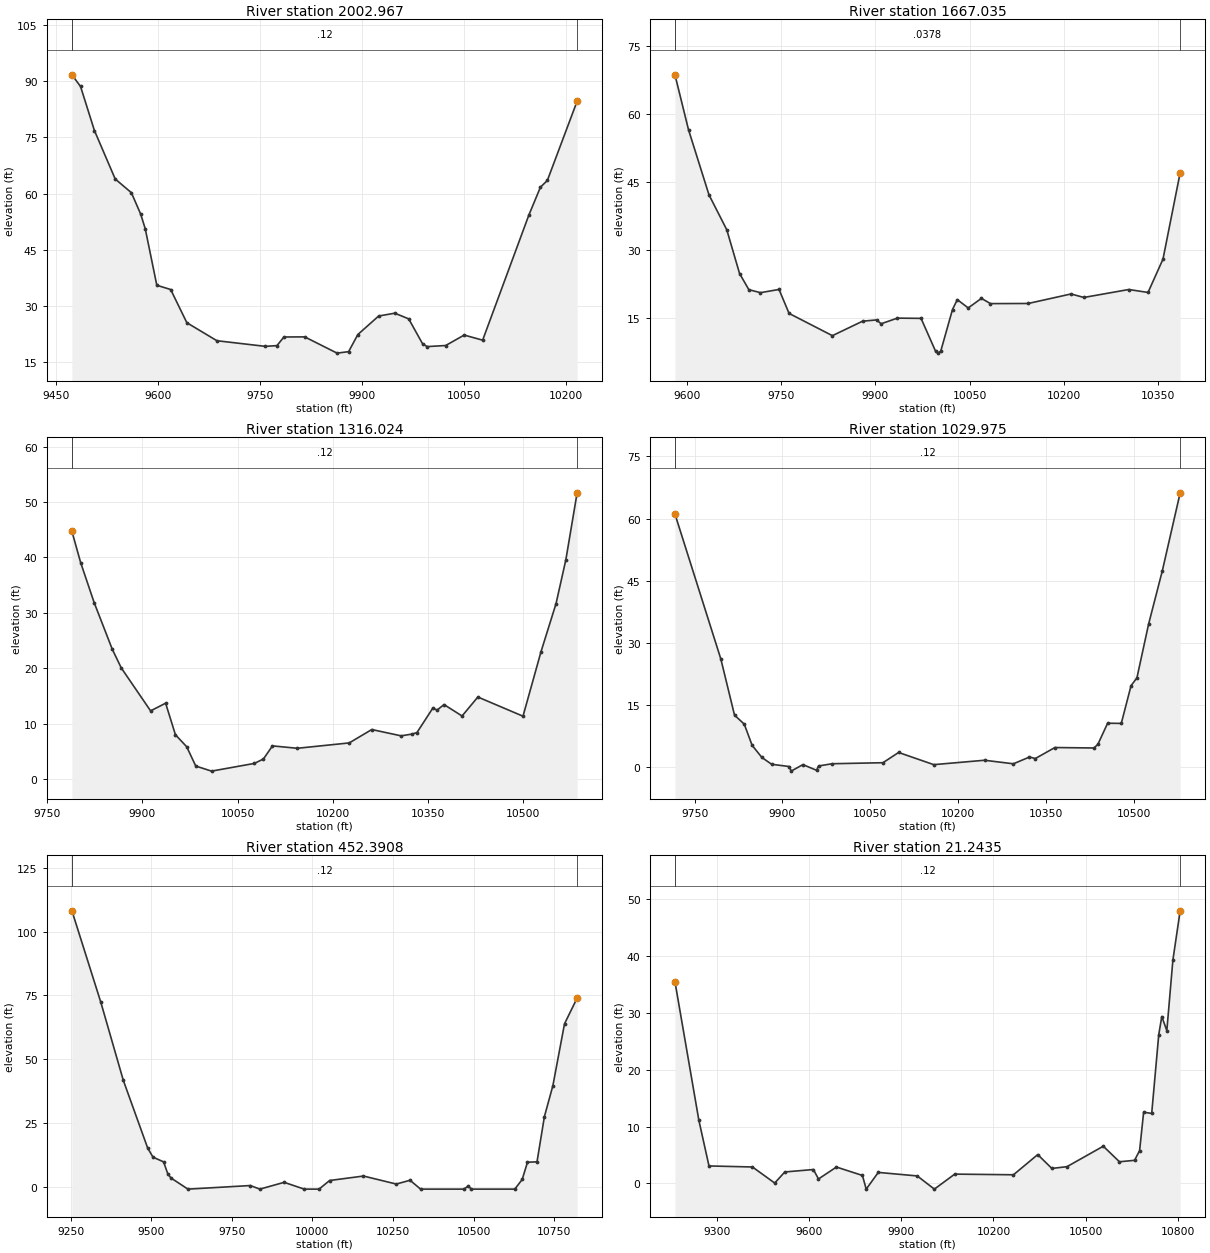
Type RM Length L Ch R = 1 ,2002.967,335.932200,335.932200,335.932200
XS GIS Cut Line= 2
1237517.26477662 836348.318531251236800.03387384836546.886239583
#Sta/Elev= 30
9472.73291.668669485.42788.559269505.85376.812829536.49163.878599560.32160.21932
9573.93854.548579580.74650.602189597.76735.527749618.19334.391579642.02325.53154
9686.27820.732059757.76719.223239774.78819.427919785.00121.724649815.63921.75531
9863.299 17.4205 9880.3217.815079893.93722.385539924.57527.321419948.40528.07628
 9968.83 26.55889989.25619.919139996.06419.16443 10023.319.4512610050.5322.23769
10077.7720.8797410145.8554.2587810162.8761.6850210173.0963.4940410216.9484.63739
#Mann= 3 , 0 , 0
9472.732    0.12       09472.732    0.12       010216.94    0.12       0
#XS Ineff= 2 , 0
       09834.869        10037.35       0
Bank Sta=9472.732,10216.94
Exp/Cntr=0.3,0.1

Type RM Length L Ch R = 1 ,1667.035,351.011200,351.011200,351.011200
XS GIS Cut Line= 6
1237353.57192361835977.7485081021237021.54067361836150.925591435
1236925.29179085836210.1598555451236847.15482291836241.388554398
1236822.84926735836288.2635543981236773.77519328836462.250822917
#Sta/Elev= 30
 9580.4268.566069602.01456.464629634.66942.095259663.04734.38657 9683.4224.73751
9698.22121.181959716.72220.518379746.32421.227319762.37115.94005 9831.4311.03348
9879.53414.225959901.73614.505569909.136 13.66199935.03814.901979972.74514.84851
9995.8597.6140589999.712 7.1819210004.117.59760210022.8916.8021210030.5318.98491
10047.9317.1487410068.9819.26213 10083.418.1031110143.5918.1320910211.86 20.2324
10232.3119.46004 10303.9 21.214310334.5820.5632610358.4427.9138510385.81 46.9769
#Mann= 3 , 0 , 0
 9580.42  0.0378       0 9580.42  0.0378       010385.81  0.0378       0
#XS Ineff= 2 , 0
       0                 10040.2       0
Bank Sta=9580.42,10385.81
Exp/Cntr=0.3,0.1

Type RM Length L Ch R = 1 ,1316.024,286.048700,286.048700,286.048700
XS GIS Cut Line= 2
1236903.05109027835704.7450358791236593.15525694 836439.12003588
#Sta/Elev= 30
9788.728 44.70759802.46739.076719823.83331.830769852.32123.432199866.56520.04534
9912.85812.283239936.54413.668959952.0287.9704759969.8335.8014829984.0772.320275
   100091.39906210076.662.79342110090.913.59936610105.155.95943210144.325.525461
10226.226.49334510261.838.91234910308.137.77301510325.938.10563310333.168.370477
10357.9812.75568 10365.112.4405110375.7913.4238910404.2711.35938 10429.214.78632
10500.4211.3207410528.9123.0058610552.5631.6696710568.0839.6117510585.8151.67106
#Mann= 3 , 0 , 0
9788.728    0.12       09788.728    0.12       010585.81    0.12       0
#XS Ineff= 2 , 0
       0                10118.37       0
Bank Sta=9788.728,10585.81
Exp/Cntr=0.3,0.1

Type RM Length L Ch R = 1 ,1029.975,577.584300,577.584300,577.584300
XS GIS Cut Line= 2
1236590.81621033835600.955146834 1236432.3960714836449.479452401
#Sta/Elev= 30
9716.42761.089969794.83726.07327  9818.212.522789834.88710.339489848.2375.244008
9864.9252.3019269881.6120.658901 9911.650.1066119914.988  -0.9999935.0130.575759
9958.376-0.797289961.713 0.244239985.0760.78761310071.851.03291310098.553.507405
10158.630.565651 10245.41.62809410294.68 0.7706310322.17 2.4079810332.182.044528
10365.554.698596 10432.34.59264110438.985.45358210455.6710.5690610479.0310.52607
10495.7219.6439910505.7321.5121810525.7534.5424310549.1247.3649310579.61 66.2125
#Mann= 3 , 0 , 0
9716.427    0.12       09716.427    0.12       010579.61    0.12       0
#XS Ineff= 2 , 0
       0                10160.05       0
Bank Sta=9716.427,10579.61
Exp/Cntr=0.3,0.1

Type RM Length L Ch R = 1 ,452.3908,431.147300,431.147300,431.147300
XS GIS Cut Line= 6
1236184.24034631834899.9646761141236163.26605707 835058.29100138
1236152.00089534835179.8865325341236146.61749754835273.605260231
1236143.99377993  835682.18581881236108.78025694836465.161702547
#Sta/Elev= 30
9253.425108.14099343.29772.201019412.79741.707739488.58115.093769505.05511.54575
9537.9979.6842589551.142  4.9231    95613.363254 9613.58  -0.9999807.2080.408163
9836.737  -0.9999912.2011.6664619974.546  -0.99910020.49  -0.99910053.322.382353
10158.424.13454110260.22 0.9898310302.922.47679910335.76  -0.99910470.41  -0.999
10483.550.229251 10493.4  -0.99910628.05  -0.99910651.04 2.7856810667.469.556012
10697.029.70296710720.0127.4500310746.2839.57915 10782.463.8419610821.5473.93462
#Mann= 3 , 0 , 0
9253.425    0.12       09253.425    0.12       010821.54    0.12       0
#XS Ineff= 2 , 0
       09924.466        10069.69       0
Bank Sta=9253.425,10821.54
Exp/Cntr=0.3,0.1

Type RM Length L Ch R = 1 , 21.2435,0.000000,0.000000,0.000000
XS GIS Cut Line= 6
 1235916.7728785834963.9579988421235941.94468254 835359.20167461
1235918.07315475835482.8995912971235826.92732143835778.038480192
1235710.00023812835979.2971607451235722.76065478836557.986396849
#Sta/Elev= 30
9162.94435.484519240.81611.100299273.7363.0777179415.2912.8967169487.7150.071164
9520.6352.0189629613.6092.4497779630.3160.7896139688.7022.8842649773.2761.408284
9785.698  -0.9999824.9411.9421219951.9081.31975710007.54  -0.99910073.891.640875
10265.171.52463110344.145.07519810390.122.63896210439.372.95046210557.596.549278
10610.133.81259210659.394.06781310675.815.77606510688.9512.5340810715.2212.31027
 10738.226.1852510748.0629.3559510764.4826.8768810784.1839.2789710807.8647.94634
#Mann= 3 , 0 , 0
9162.944    0.12       09162.944    0.12       010807.86    0.12       0
#XS Ineff= 2 , 0
       09959.171        10133.62       0
Bank Sta=9162.944,10807.86
Exp/Cntr=0.3,0.1